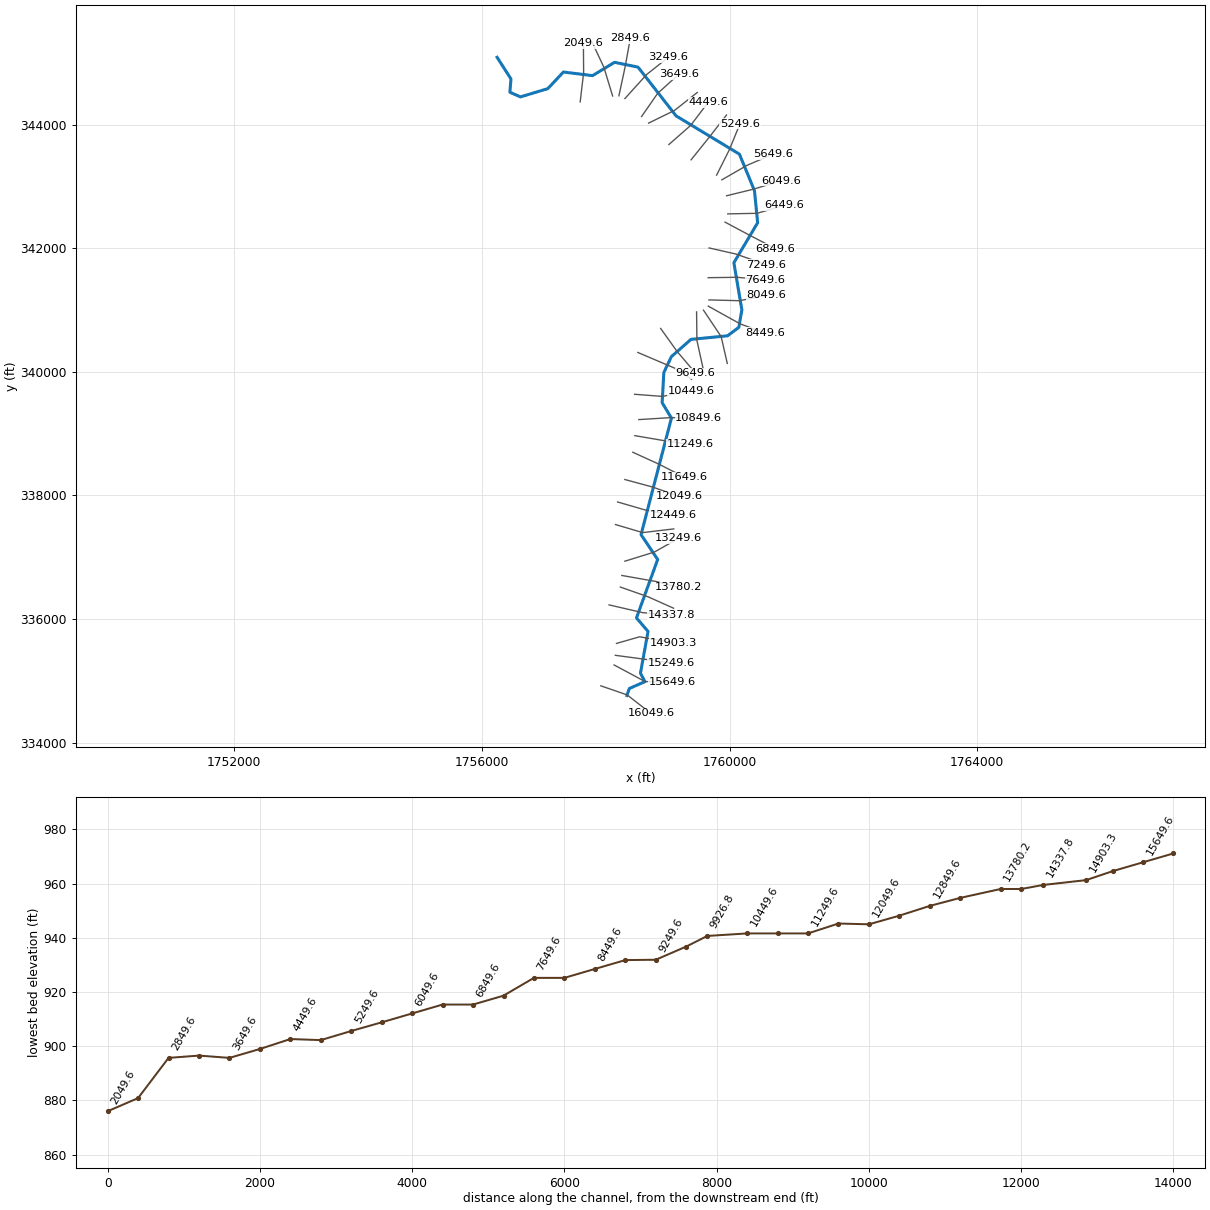
--- CnsRn.prj (project) ---

Proj Title=CnsRn
Current Plan=p01
Default Exp/Contr=0,0
English Units
Geom File=g01
Flow File=f01
Plan File=p01
BEGIN DESCRIPTION:
END DESCRIPTION:
DSS Export Rating Curves= 0
DSS Export Rating Curve Sorted= 0
DSS Export Volume Flow Curves= 0
DXF OffsetX= 0
DXF OffsetY= 0
DXF ScaleX= 0
DXF ScaleY= 0

--- CnsRn.p01 (plan) ---

Plan Title=Floodplain
Program Version=4.00
Geom File=g01
Flow File=f01
K Sum by GR=0
Std Step Tol=0.01
Critical Tol=0.01
Num of Std Step Trials=20
Max Error Tol=0.3
Flow Tol Ratio=0.001
Split Flow NTrial=30
Split Flow Tol=0.02
Split Flow Ratio=0.02
Log Output Level=0
Friction Slope Method=1
Unsteady Friction Slope Method=2
Unsteady Bridges Friction Slope Method=1
Global Log Level=0
CheckData=False
Run HTab=0
Run UNet=0
Run PostProcess=0
UNET Theta=0
UNET Theta Warmup=0
UNET ZTol=0
UNET ZSATol=0
UNET MxIter=0
UNET MaxInSteps=0
UNET DtIC=0
UNET DtMin=0
UNET MaxCRTS=0
UNET WFStab=0
UNET SFStab=0
UNET WFX=0
UNET SFX=0
UNET DSS MLevel=0
UNET DZMax Abort=0
UNET Convert EG Bridges=0
UNET Use Existing IB Tables=0
UNET Froude Limit=0
UNET Froude Power=0
Write IC File=0
Echo Input=False
Echo Output=False
Write Detailed=0

--- CnsRn.f01 (steady flow) ---

Flow Title=NFF Regression Equation
Program Version=4.00
Number of Profiles=1
Profile Names=P100yr
River Rch & RM=CnsRn,Main      ,16049.6
1440.775
River Rch & RM=CnsRn,Main      ,13249.6
1557.898
River Rch & RM=CnsRn,Main      ,11249.6
1695.746
River Rch & RM=CnsRn,Main      ,7649.6
1882.588
River Rch & RM=CnsRn,Main      ,321.2
2076.330
River Rch & RM=CnsRn,Main      ,92.4
2076.330
Boundary for River Rch & Prof#=CnsRn,Main      ,1
Up Type=0
Dn Type=3
Dn Slope=0.008728

--- CnsRn.g01 (geometry) ---

Geom Title=USGS 3m DEM
Program Version=4.00

River Reach=CnsRn           ,Main
Reach XY= 30
     1758342.047      334763.204     1758380.999      334876.164
     1758634.187      334987.177     1758560.178      335123.509
     1758682.877      335799.326     1758495.907      336017.457
     1758838.685       336963.99     1758569.916      337365.196
     1759060.711      339250.471     1758910.746      339499.764
     1758938.012      339988.611     1759060.711      340245.694
     1759376.222      340524.201     1759968.292      340582.629
     1760149.418      340718.961     1760198.109      341001.363
     1760069.749      341764.633     1760453.567      342412.027
     1760401.628      342931.839     1760158.843      343521.178
      1759135.93       344140.21     1758520.918      344929.257
     1758142.246      345006.766     1757786.203      344791.306
     1757316.348      344850.038     1757064.639      344581.549
     1756622.751      344447.305     1756452.149      344522.817
      1756468.93      344738.168     1756245.188      345087.762

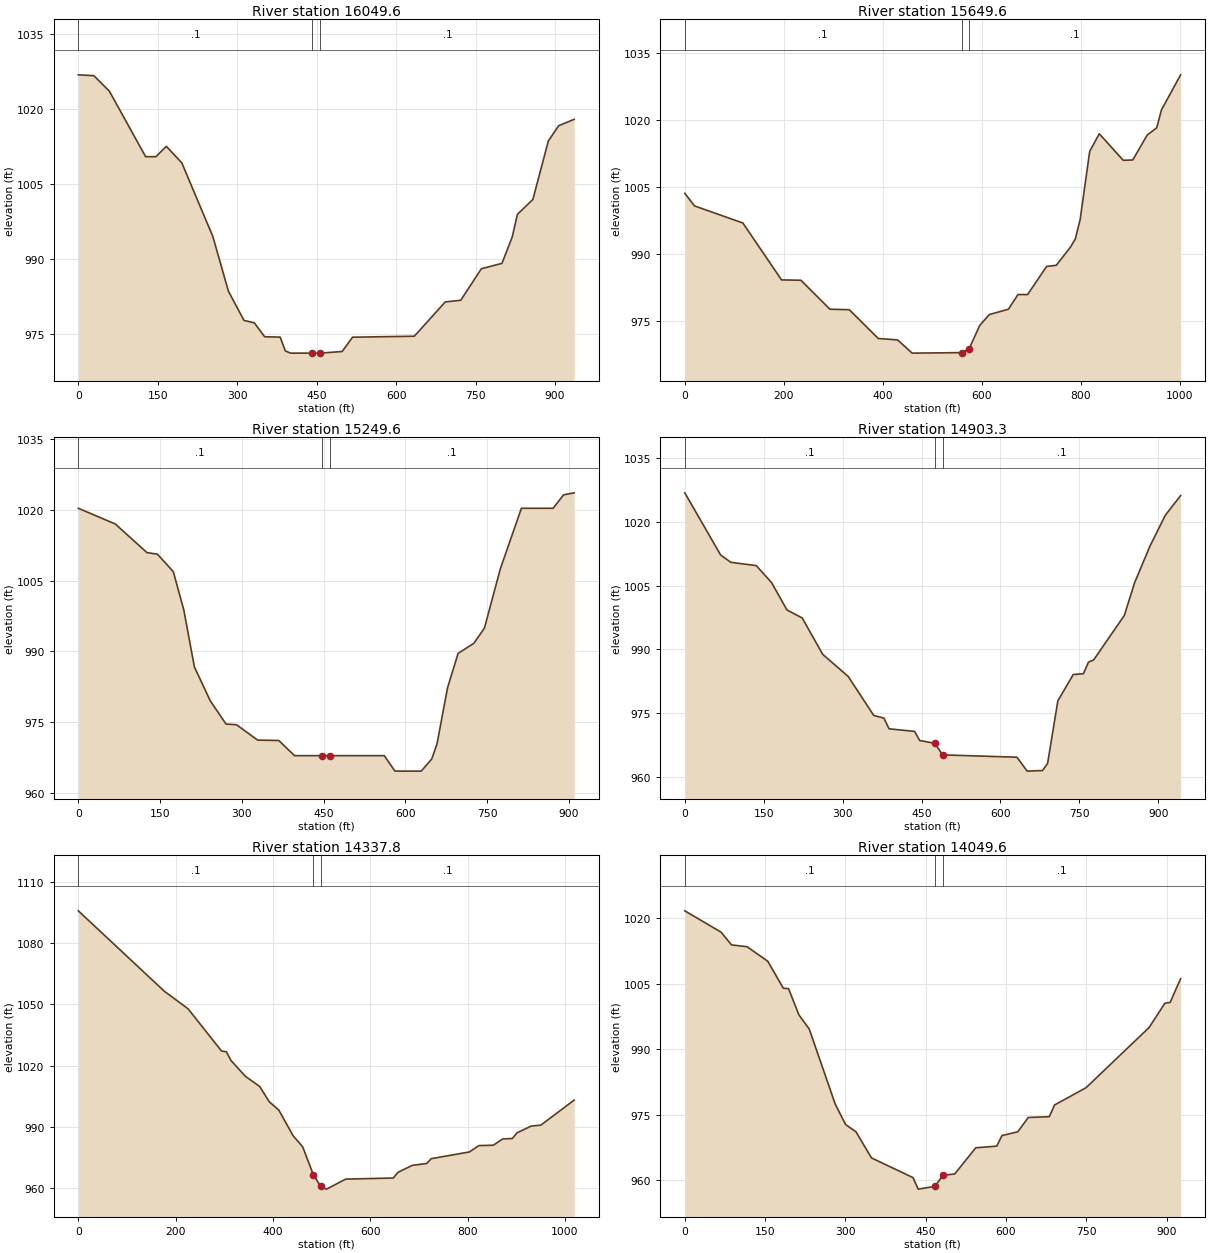
Type RM Length L Ch R = 1 ,16049.6 ,405.351,400,412.962
XS GIS Cut Line= 3
      1757920.42       334919.17     1758345.307      334772.657
     1758729.031      334473.572
#Sta/Elev= 30
       0  1026.9    29.3 1026.73    58.6 1023.62     127  1010.5   146.6  1010.5
   166.1 1012.58   195.4 1009.25     254  994.48   283.3  983.55   312.7  977.69
   332.2   977.2   351.7  974.41     381  974.34   390.8  971.58   400.6  971.13
   441.9  971.13   456.9  971.13   498.1  971.46   517.6  974.32   634.3  974.52
   692.7  981.39   721.9  981.72   760.8  988.04   799.7  989.12   819.2  994.44
   828.9  998.94   858.1 1001.93   887.3 1013.66   906.8  1016.7     936 1017.98
#Mann= 3 , 0 , 0
       0      .1       0   441.9    .045       0   456.9      .1       0
Bank Sta=441.9,456.9
XS Rating Curve= 0 ,0
Exp/Cntr=0.3,0.1

Type RM Length L Ch R = 1 ,15649.6 ,391.873,400,396.075
XS GIS Cut Line= 3
     1758134.562      335257.056     1758634.187      334988.963
     1759068.949       334974.73
#Sta/Elev= 30
       0 1003.66    19.6 1000.84   117.3  997.01   195.5  984.26   234.6  984.18
   293.3  977.69   332.4  977.58     391  971.13   430.1  970.81   459.5  967.85
   559.5  967.96   574.5  968.81     596  974.05   615.3  976.49     654  977.69
   673.3  980.97   692.7  980.97   731.3  987.28   750.7  987.53   779.7  991.65
   789.3  993.46     799  997.81   818.3 1013.09   837.7    1017     886 1011.06
   905.3 1011.13   934.3 1016.69   953.7 1018.35   963.3 1022.36    1002 1030.21
#Mann= 3 , 0 , 0
       0      .1       0   559.5    .045       0   574.5      .1       0
Bank Sta=559.5,574.5
XS Rating Curve= 0 ,0
Exp/Cntr=0.3,0.1

Type RM Length L Ch R = 1 ,15249.6 ,347.367,346.34,345.313
XS GIS Cut Line= 3
     1758154.691      335412.891     1758605.659      335352.452
     1759056.627      335292.012
#Sta/Elev= 30
       0 1020.34    67.8 1017.01   125.9 1010.94   145.2  1010.6   174.3  1006.9
   193.6  998.77     213  986.69     242  979.52   271.1  974.56   290.4  974.41
   329.1  971.15   367.9  971.07   396.9  967.85   447.5  967.85   462.5  967.85
   561.5  967.85   580.9   964.6   590.5  964.57   629.3  964.57   648.6  967.13
   658.3  970.34   677.7  982.29     697  989.55   726.1  991.71   745.4  994.94
   774.5 1007.49   813.2 1020.34   871.3 1020.34   890.6 1023.19     910 1023.62
#Mann= 3 , 0 , 0
       0      .1       0   447.5    .045       0   462.5      .1       0
Bank Sta=447.5,462.5
XS Rating Curve= 0 ,0
Exp/Cntr=0.3,0.1

Type RM Length L Ch R = 1 ,14903.3 ,590.53,565.488,554.976
XS GIS Cut Line= 3
     1758173.635       335605.22     1758546.831      335712.531
     1759092.746       335616.81
#Sta/Elev= 30
       0 1026.88      68 1012.25    87.4 1010.51   135.9 1009.72     165 1005.71
   194.2  999.28   223.3  997.37   262.1  988.82   310.7  983.59   359.2  974.41
   378.6  973.77   388.3  971.26   436.9  970.64   446.7  968.48   475.2  967.85
   490.2  965.11   631.4  964.56   650.9  961.28     680  961.42   689.7  963.08
   709.2  977.84   738.4  984.04   757.8  984.25   767.5  986.98   777.3   987.5
   835.6  997.98     855 1005.65   884.2 1014.29   913.4 1021.57   942.6 1026.24
#Mann= 3 , 0 , 0
       0      .1       0   475.2    .045       0   490.2      .1       0
Bank Sta=475.2,490.2
XS Rating Curve= 0 ,0
Exp/Cntr=0.3,0.1

Type RM Length L Ch R = 1 ,14337.8 ,290.722,288.172,283.721
XS GIS Cut Line= 3
     1758053.533      336228.774     1758598.456      336102.581
     1759056.531      336061.857
#Sta/Elev= 30
       0 1095.77   176.6 1056.43   225.7 1047.77   294.4 1027.11   304.2 1026.79
     314 1022.42   343.5 1014.72   372.9 1009.73   392.5 1002.24   412.1  998.19
   441.6   985.6   461.2  980.18     483   966.6     498  960.84   510.3  959.48
   549.5  964.38   647.4  964.92   657.2  967.74   686.5  971.13   715.9  972.02
   725.7  974.41     804  977.69   823.5  980.81   852.9  980.97   872.5  984.07
     892  984.25   901.8  987.08   931.2  990.38   950.7  990.81  1019.2 1003.09
#Mann= 3 , 0 , 0
       0      .1       0     483    .045       0     498      .1       0
Bank Sta=483,498
XS Rating Curve= 0 ,0
Exp/Cntr=0.3,0.1

Type RM Length L Ch R = 1 ,14049.6 ,265.715,269.432,275.051
XS GIS Cut Line= 3
     1758235.671      336517.354      1758683.52      336359.712
     1759095.349      336174.826
#Sta/Elev= 30
       0 1021.75    67.8 1016.86    87.2 1013.95   116.3 1013.53     155  1010.2
   184.1 1004.01   193.8 1003.93   213.2  997.91   232.5  994.66     281  977.48
   300.4  972.79   319.8  971.13   348.8  965.14   426.3  960.64     436     958
   467.3  958.63   482.3  961.16   504.2  961.47   543.5  967.47   582.7  967.85
   592.5  970.27     622  971.13   641.6  974.41   680.9  974.59   690.7  977.27
   749.6  981.24   867.3  995.02   896.8 1000.58   906.6 1000.77   926.2  1006.2
#Mann= 3 , 0 , 0
       0      .1       0   467.3    .045       0   482.3      .1       0
Bank Sta=467.3,482.3
XS Rating Curve= 0 ,0
Exp/Cntr=0.3,0.1

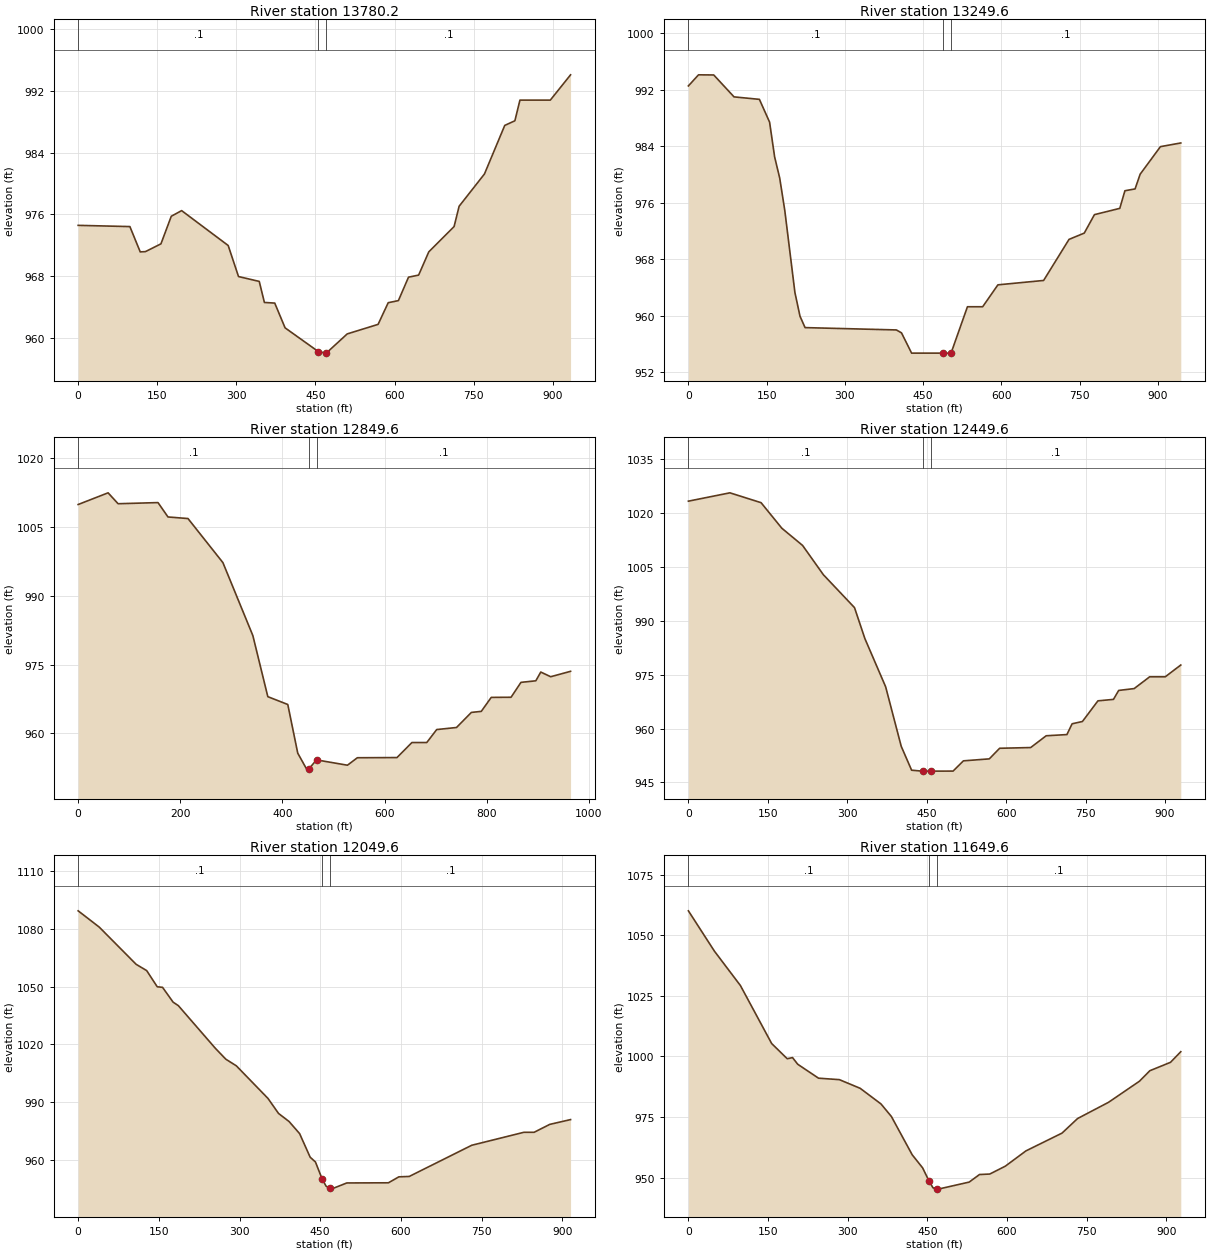
Type RM Length L Ch R = 1 ,13780.2 ,517.843,530.568,546.949
XS GIS Cut Line= 3
      1758260.03      336704.865     1758810.689      336607.352
     1759172.762      336511.236
#Sta/Elev= 30
       0  974.57    98.1  974.41   117.7  971.13   127.5  971.16     157  972.17
   176.6  975.75   196.2  976.48   284.5  971.96   304.1  967.93   343.4   967.3
   353.2  964.57   372.8  964.49   392.4  961.28   455.5   958.2   470.5     958
   510.2  960.49   568.8  961.73     588  964.54   607.3  964.81   626.5  967.85
   645.7  968.12   664.9  971.13   712.9  974.41   722.5  977.05   770.5  981.23
     809  987.53   828.2  988.13   837.8  990.81   895.4  990.81   933.8  994.09
#Mann= 3 , 0 , 0
       0      .1       0   455.5    .045       0   470.5      .1       0
Bank Sta=455.5,470.5
XS Rating Curve= 0 ,0
Exp/Cntr=0.3,0.1

Type RM Length L Ch R = 1 ,13249.6 ,415.023,400,391.606
XS GIS Cut Line= 3
     1758309.481      336935.941     1758783.086      337082.882
     1759172.912      337303.219
#Sta/Elev= 30
       0  992.52    19.4  994.09    48.6  994.07    87.5  990.97   136.1  990.62
   155.6   987.4   165.3  982.47     175  979.49   184.7  974.93   204.2  963.28
   213.9  959.94   223.6  958.33   398.6     958   408.4  957.59   427.8  954.72
   488.4  954.72   503.4  954.72   534.8  961.28     564  961.28   593.2  964.38
   680.8     965   729.5  970.81   758.7   971.7   778.2  974.31   826.8   975.2
   836.6  977.69   856.1  977.95   865.8  980.03   904.7  983.93   943.7  984.45
#Mann= 3 , 0 , 0
       0      .1       0   488.4    .045       0   503.4      .1       0
Bank Sta=488.4,503.4
XS Rating Curve= 0 ,0
Exp/Cntr=0.3,0.1

Type RM Length L Ch R = 1 ,12849.6 ,400.048,400,388.328
XS GIS Cut Line= 3
     1758157.105      337528.654     1758597.419      337398.199
     1759098.565      337458.209
#Sta/Elev= 30
       0 1009.94    58.6 1012.49    78.2 1010.11   156.3 1010.36   175.9 1007.22
     215 1006.88   283.4  997.26     342  981.34   371.3  968.01   410.4   966.3
   429.9  955.68   449.5  951.76   451.7  952.26   466.7  954.21   527.2  953.05
   546.6  954.68   624.2  954.72   653.4     958   682.5     958   701.9  960.83
   740.7  961.28   769.8  964.57   789.2   964.8   808.7  967.85   847.5  967.88
   866.9  971.13     896  971.47   905.7  973.38   925.1  972.36     964  973.54
#Mann= 3 , 0 , 0
       0      .1       0   451.7    .045       0   466.7      .1       0
Bank Sta=451.7,466.7
XS Rating Curve= 0 ,0
Exp/Cntr=0.3,0.1

Type RM Length L Ch R = 1 ,12449.6 ,399.65,400,396.695
XS GIS Cut Line= 3
     1758191.155      337894.008     1758624.018      337768.084
     1759093.768      337675.644
#Sta/Elev= 30
       0 1023.28    78.4  1025.6   137.2 1022.86   176.4 1015.75   215.6 1010.96
   254.8 1002.82   313.6  993.66   333.2  985.04   372.4  971.63   401.8  955.07
   421.4  948.42     441  948.16   443.3  948.16   458.3  948.16   499.7  948.17
   519.2  951.02   568.1  951.57   587.6  954.52   646.2  954.72   675.5     958
   714.6  958.33   724.4  961.33   743.9  961.97   773.2  967.72   802.5  968.12
   812.3  970.61   841.6  971.13   870.9  974.41   900.3  974.41   929.6  977.69
#Mann= 3 , 0 , 0
       0      .1       0   443.3    .045       0   458.3      .1       0
Bank Sta=443.3,458.3
XS Rating Curve= 0 ,0
Exp/Cntr=0.3,0.1

Type RM Length L Ch R = 1 ,12049.6 ,402.568,400,397.711
XS GIS Cut Line= 3
     1758308.292      338257.009     1758752.988       338136.44
     1759182.088      337986.056
#Sta/Elev= 30
       0 1089.24    39.2  1080.8   107.8 1061.51   127.4 1058.25     147 1049.87
   156.9 1049.57   176.5 1041.89   186.3 1040.07   254.9 1018.02   274.5 1012.32
   294.1 1008.88   352.9  991.98   372.5   984.2   392.1  980.01   411.7  973.74
   431.3  961.51   441.1  959.05   453.3  950.41   460.8  946.53   468.3   945.3
   470.4  944.96   499.4  948.16   576.8  948.24   596.2  951.33   615.5  951.53
   731.6  967.69   828.4  974.41   847.7  974.43   876.7  978.52   915.4  981.01
#Mann= 3 , 0 , 0
       0      .1       0   453.3    .045       0   468.3      .1       0
Bank Sta=453.3,468.3
XS Rating Curve= 0 ,0
Exp/Cntr=0.3,0.1

Type RM Length L Ch R = 1 ,11649.6 ,393.839,400,407.823
XS GIS Cut Line= 3
     1758436.707      338698.215     1758855.966      338507.205
     1759271.245      338294.522
#Sta/Elev= 30
       0 1060.03      49 1043.41      98 1029.21   156.8 1005.31   186.2  999.02
   196.1  999.51   205.9  996.76   245.1  991.01   284.3  990.41   323.5  986.84
   362.7  980.39   382.3  975.21   421.5  959.42   441.1  954.03   453.2   948.6
   460.7  945.79   468.2  945.38   470.4  945.26   528.8  948.16   548.2  951.28
   567.6  951.48   596.8  954.72   635.7  961.03   703.7  968.37   732.9  974.37
   791.2  981.06   849.5  989.77     869  994.09   907.9  997.55   927.3 1001.93
#Mann= 3 , 0 , 0
       0      .1       0   453.2    .045       0   468.2      .1       0
Bank Sta=453.2,468.2
XS Rating Curve= 0 ,0
Exp/Cntr=0.3,0.1

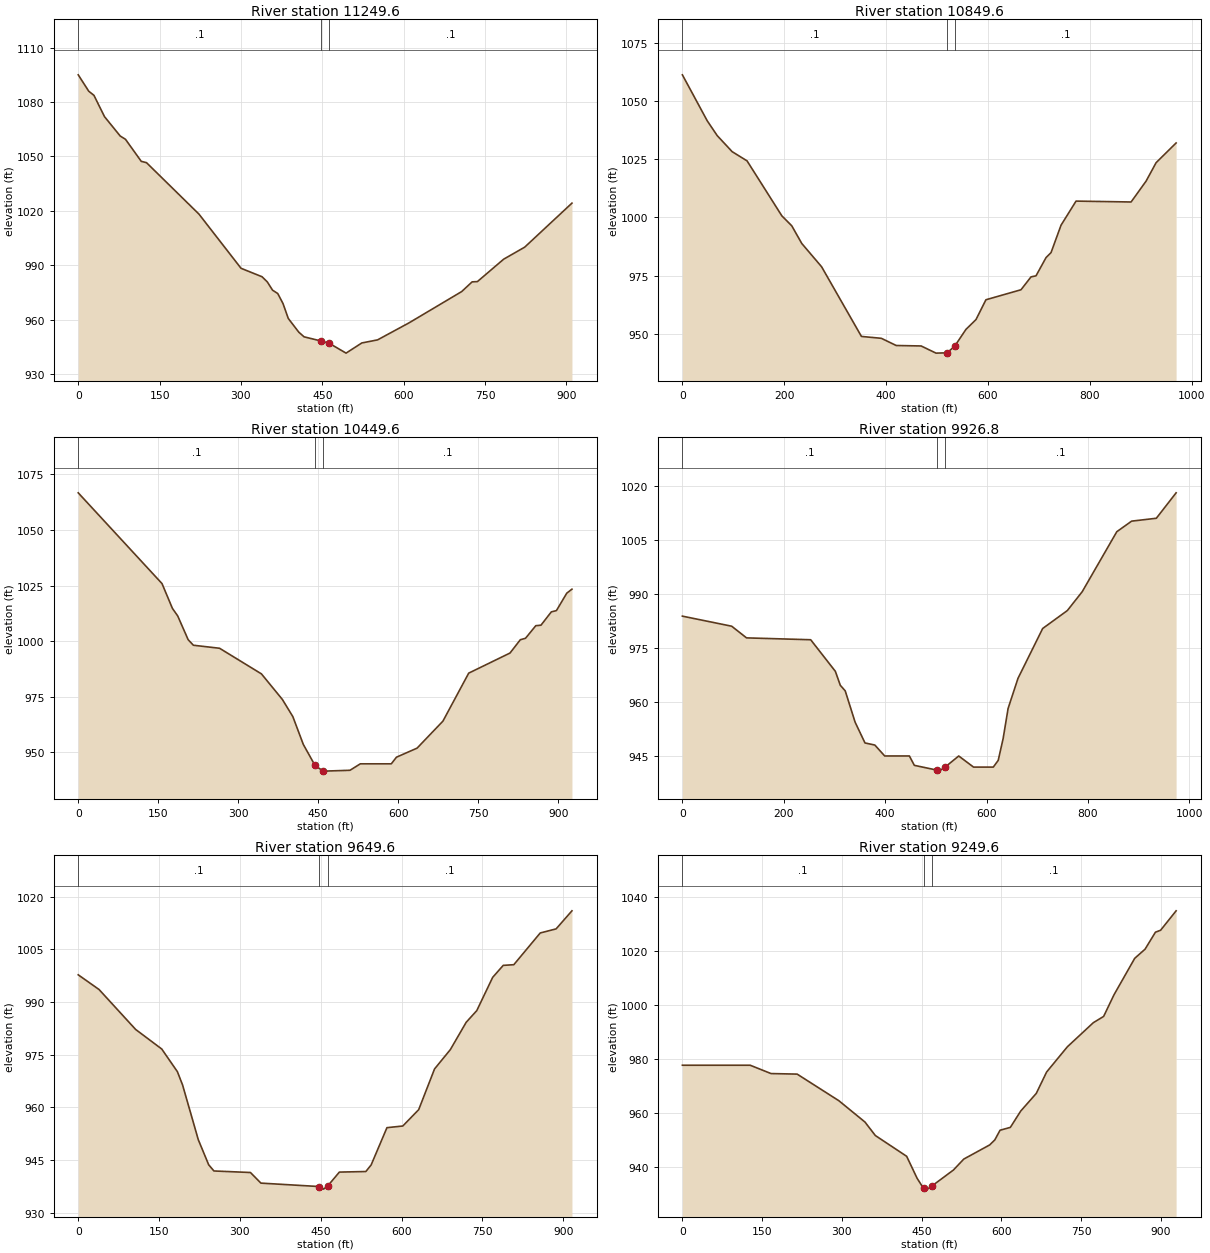
Type RM Length L Ch R = 1 ,11249.6 ,394.508,400,402.817
XS GIS Cut Line= 3
     1758469.958      338967.058     1758918.354       338889.99
     1759368.688      338823.858
#Sta/Elev= 30
       0 1094.99    19.4 1085.96      29 1083.68    48.4 1071.96    77.4 1061.26
    87.1 1059.46   116.2  1047.3   125.8 1046.59   222.6 1018.21   300.1  988.36
   338.8   983.7   348.5  980.87   358.2  976.31   367.8  974.44   377.5   968.9
   387.2  960.71   406.6  953.14   416.3  950.59   447.5  948.29   462.5  947.06
   493.7   941.6   522.8  947.21   551.8   948.9   609.9   958.3   706.8  975.52
   726.1  980.88   735.8  981.02   784.2  993.37     823 1000.01   910.1 1024.27
#Mann= 3 , 0 , 0
       0      .1       0   447.5    .045       0   462.5      .1       0
Bank Sta=447.5,462.5
XS Rating Curve= 0 ,0
Exp/Cntr=0.3,0.1

Type RM Length L Ch R = 1 ,10849.6 ,404.371,400,403.948
XS GIS Cut Line= 3
     1758534.357      339226.667     1759060.711      339259.144
     1759502.653      339244.676
#Sta/Elev= 30
       0 1061.36    48.8 1041.57    68.4  1035.2    97.7  1028.3     127 1024.33
   195.3 1000.68   214.8  996.39   234.4   988.8   273.4  978.75   351.6  948.78
   390.6  947.98   419.9  944.88   468.8  944.68   498.1   941.6   519.9  941.73
   534.9  944.64   556.8  951.81   576.5  956.03   596.1  964.57   664.9  968.87
   684.6  974.41   694.4  974.87   714.1  982.72   723.9  984.85   743.5  996.64
     773 1007.02   881.1 1006.64   910.6 1015.64   930.2 1023.55   969.5 1032.04
#Mann= 3 , 0 , 0
       0      .1       0   519.9    .045       0   534.9      .1       0
Bank Sta=519.9,534.9
XS Rating Curve= 0 ,0
Exp/Cntr=0.3,0.1

Type RM Length L Ch R = 1 ,10449.6 ,530.128,522.744,508.929
XS GIS Cut Line= 3
     1758465.613      339636.197     1758915.879       339601.56
     1759380.556      339696.555
#Sta/Elev= 30
       0 1066.73   157.1 1025.93   176.7 1014.75   186.5 1011.41   206.2 1000.68
     216   998.2   265.1  996.84   343.6  985.32   382.9  973.81   402.5   966.1
   422.1  953.61   444.1  944.14   459.1  941.65   461.3   941.6   509.7  941.98
     529  944.88   587.1  944.88   596.8  947.87   635.5  951.94   683.9  964.07
   732.3  985.66   809.7  994.69   829.1 1000.68   838.8 1001.33   858.1 1006.99
   867.8 1007.22   887.2  1013.2   896.8 1013.78   916.2 1021.62   925.9 1023.41
#Mann= 3 , 0 , 0
       0      .1       0   444.1    .045       0   459.1      .1       0
Bank Sta=444.1,459.1
XS Rating Curve= 0 ,0
Exp/Cntr=0.3,0.1

Type RM Length L Ch R = 1 ,9926.8  ,289.652,277.256,266.751
XS GIS Cut Line= 3
     1758518.151      340312.827     1759108.962      340060.442
     1759386.839      339879.747
#Sta/Elev= 30
       0  983.75    97.3  980.95   126.5  977.71   253.1  977.19   301.8   968.4
   311.5  964.53   321.2  962.98   340.7  954.28   360.2   948.5   379.6  947.92
   399.1  944.88   447.8  944.88   457.5  942.28   502.8  940.93   506.2  940.67
   517.8  941.74   545.1  944.88   574.3  941.79   613.3  941.79     623  943.66
   632.7  949.73   642.5   958.1     662  966.46   710.7  980.32   759.4  985.31
   788.7  990.55   856.9 1007.22   886.2 1010.16   934.9 1010.96   973.9 1018.03
#Mann= 3 , 0 , 0
       0      .1       0   502.8    .045       0   517.8      .1       0
Bank Sta=502.8,517.8
XS Rating Curve= 0 ,0
Exp/Cntr=0.3,0.1

Type RM Length L Ch R = 1 ,9649.6  ,414.627,400,388.487
XS GIS Cut Line= 3
     1758886.854      340700.932      1759151.33      340330.429
     1759449.311      339978.729
#Sta/Elev= 30
       0  997.77    38.7  993.58   106.5  982.22     155  976.64     184   970.2
   193.7  966.38   222.8  950.83   242.1  943.68   251.8  941.92   319.6  941.48
     339  938.46   447.7  937.48   455.2  936.75   462.7   937.6   484.6   941.6
   533.7  941.76   543.5  943.62   572.9  954.25   602.3  954.72   631.8  959.38
   661.2  970.96   690.6  976.49     720  984.27   739.6  987.58   769.1  997.05
   788.7 1000.46   808.3 1000.65   857.3 1009.68   886.8 1010.85   916.2 1015.99
#Mann= 3 , 0 , 0
       0      .1       0   447.7    .045       0   462.7      .1       0
Bank Sta=447.7,462.7
XS Rating Curve= 0 ,0
Exp/Cntr=0.3,0.1

Type RM Length L Ch R = 1 ,9249.6  ,386.858,400,399.77
XS GIS Cut Line= 3
     1759466.964      340969.152     1759472.322      340508.184
     1759572.649      340051.563
#Sta/Elev= 30
       0  977.69   127.5  977.69   166.7  974.61   215.8  974.41   294.3  964.57
   343.3   956.7   362.9   951.7   421.8  944.02   441.4   935.9   453.5  932.17
     461  931.89   468.5  932.94   509.7  938.95   529.2     943   577.9  948.23
   587.6   950.1   597.4  953.66   616.8  954.72   636.3  960.76   665.5  967.27
     685  975.19     724  984.51   772.7   993.4   792.2  995.74   811.6  1003.7
   850.6  1017.2   870.1 1020.59   889.6 1026.87   899.3 1027.59   928.5 1034.77
#Mann= 3 , 0 , 0
       0      .1       0   453.5    .045       0   468.5      .1       0
Bank Sta=453.5,468.5
XS Rating Curve= 0 ,0
Exp/Cntr=0.3,0.1

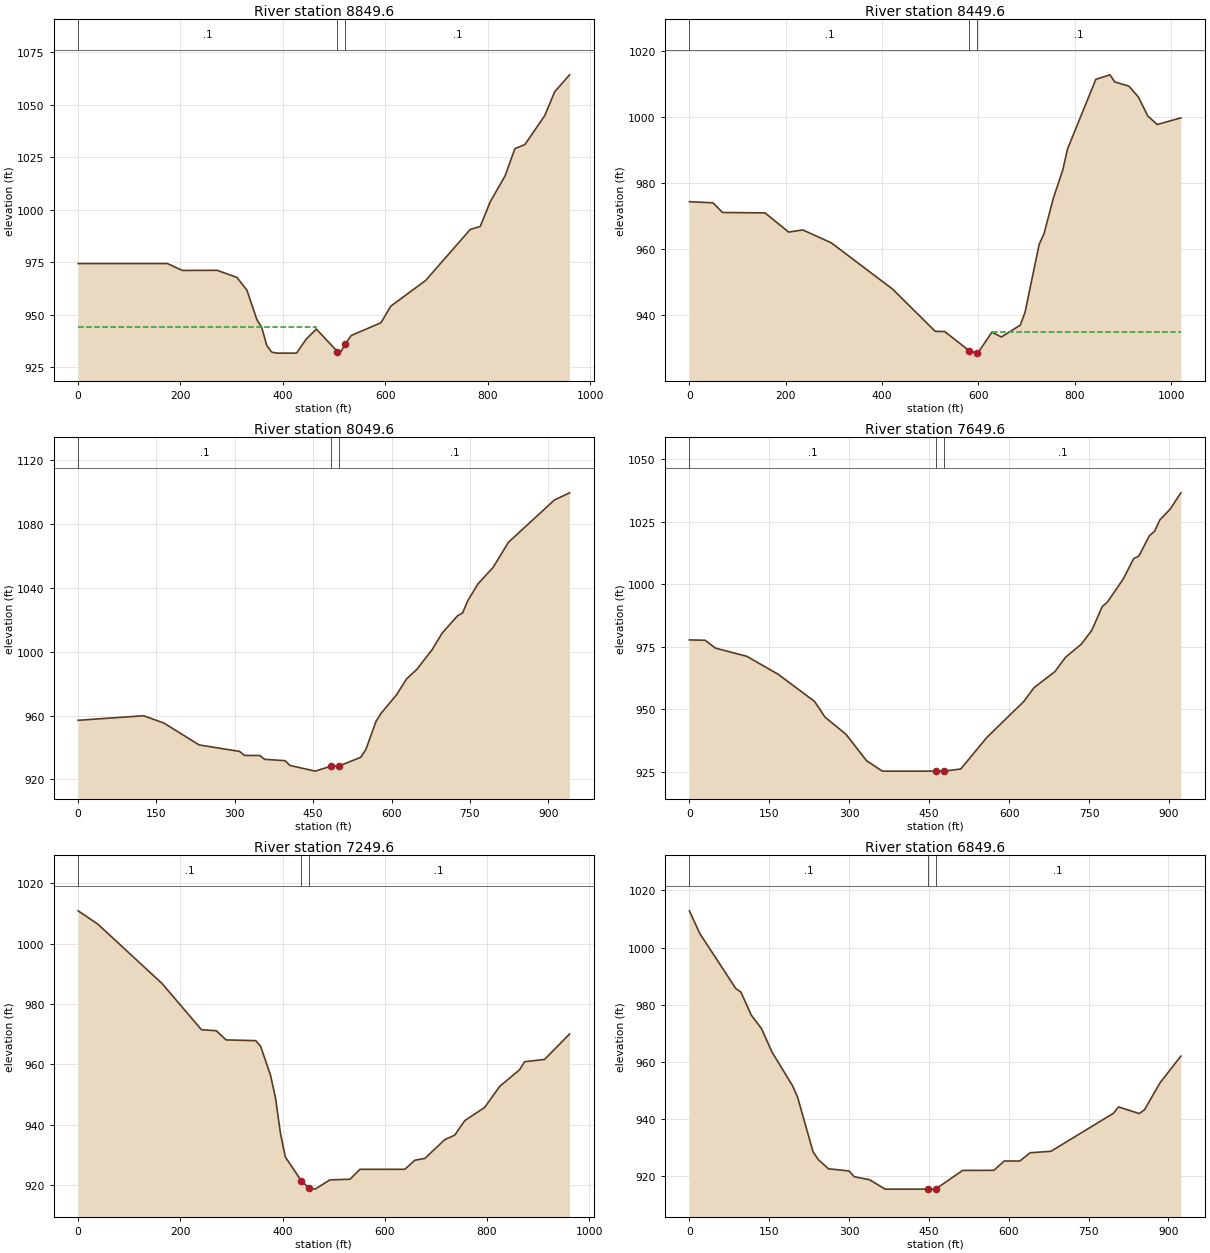
Type RM Length L Ch R = 1 ,8849.6  ,389.14,400,422.734
XS GIS Cut Line= 3
     1759578.737      340996.928     1759863.808      340569.205
     1759963.188      340134.446
#Sta/Elev= 30
       0  974.41   174.6  974.41   203.7  971.14   271.6   971.2   310.3  967.81
   329.7  961.77   349.1  947.79   358.8  943.92   368.5  935.45   378.2  932.25
   387.9  931.76   426.7  931.76   446.1   938.6   465.5   943.2   506.5  932.51
     514  932.73   521.5  935.91   533.4  940.14   591.6  946.24     611  954.18
   678.8  966.33   766.1  990.68   785.5  992.07   804.9 1003.76     834 1016.15
   853.3 1029.16   872.7 1031.06   911.5 1044.85   930.9 1056.19     960  1064.3
#Mann= 3 , 0 , 0
       0      .1       0   506.5    .045       0   521.5      .1       0
#XS Ineff= 2 , 0
          465.01  944.21
Permanent Ineff=
       F       F
Bank Sta=506.5,521.5
XS Rating Curve= 0 ,0
Exp/Cntr=0.3,0.1

Type RM Length L Ch R = 1 ,8449.6  ,389.713,400,411.794
XS GIS Cut Line= 3
     1759655.705      341061.841     1760170.296      340775.627
     1760575.081      340626.496
#Sta/Elev= 30
       0  974.41    49.1  974.05    68.7  971.13     157     971   206.1  965.19
   235.5  965.84   294.4  961.94     422  947.88   510.3   935.1   529.9  935.04
   581.3  929.17   596.3   928.5   598.6  928.49     628  934.84   647.7  933.38
   686.9  936.98   696.7  940.82   726.1  961.49   735.9  964.56   755.5  975.43
   775.1  984.02   784.9  990.36   843.7 1011.49   873.2 1012.86     883  1010.7
   912.4 1009.44     932 1006.15   951.6 1000.38   971.2   997.8  1020.2  999.81
#Mann= 3 , 0 , 0
       0      .1       0   581.3    .045       0   596.3      .1       0
#XS Ineff= 2 , 0
                          628.04          934.88
Permanent Ineff=
       F       F
Bank Sta=581.3,596.3
XS Rating Curve= 0 ,0
Exp/Cntr=0.3,0.1

Type RM Length L Ch R = 1 ,8049.6  ,400.068,400,392.454
XS GIS Cut Line= 3
     1759666.185      341162.861     1760158.432      341150.052
     1760598.486       341236.15
#Sta/Elev= 30
       0  957.04   125.5  959.89   164.1  955.33   231.7   941.6     309  937.55
   318.6  935.04   347.6  934.99   357.2  932.59   395.9  931.76   405.5  928.79
   453.8   925.2   484.9  928.37   499.9  928.48   541.2  933.88   550.9  938.76
   570.4  956.42   580.1  961.44   609.4  972.94   628.9  982.97   648.4  988.94
   677.6 1001.22   697.1 1011.73   726.4 1022.48   736.1 1024.36   745.9 1031.93
   765.4 1042.42   794.6 1052.86   823.8 1068.53   911.6 1094.97   940.8 1099.51
#Mann= 3 , 0 , 0
       0      .1       0   484.9    .045       0   499.9      .1       0
Bank Sta=484.9,499.9
XS Rating Curve= 0 ,0
Exp/Cntr=0.3,0.1

Type RM Length L Ch R = 1 ,7649.6  ,404.772,400,395.133
XS GIS Cut Line= 3
      1759654.75      341522.454     1760124.466      341528.954
     1760574.809      341485.916
#Sta/Elev= 30
       0  977.69    29.4  977.56    48.9  974.41   107.7  971.13   166.4  963.96
   234.9  953.08   254.5  946.79   293.6  939.99   332.7  929.31   362.1   925.2
   462.3   925.2   477.3   925.2   509.1  926.04   558.3  938.72   627.1  952.98
   646.8   958.6   686.1  965.06   705.8  970.77   735.3  975.95     755  981.49
   774.6  990.99   784.5  992.86     814 1002.01   833.6  1010.2   843.5 1011.24
   863.1 1019.34     873 1021.17   882.8 1025.69   902.5 1030.08   922.2 1036.53
#Mann= 3 , 0 , 0
       0      .1       0   462.3    .045       0   477.3      .1       0
Bank Sta=462.3,477.3
XS Rating Curve= 0 ,0
Exp/Cntr=0.3,0.1

Type RM Length L Ch R = 1 ,7249.6  ,406.074,400,396.783
XS GIS Cut Line= 3
     1759668.899      342003.864     1760101.768       341905.09
     1760589.913      341733.701
#Sta/Elev= 30
       0 1010.87    38.6 1006.46   164.1   986.8   241.3  971.47   270.3  971.13
   289.6  968.09   347.5  967.85   357.1  965.94   376.4  956.38   386.1  948.92
   395.7   937.3   405.4   929.3   436.5  921.43   451.5  919.02   463.5  918.63
   492.8   921.7   531.8  921.91   551.4   925.2   639.2   925.2   658.7   928.2
   678.3  928.81   717.3  935.04   736.8  936.53   756.4  941.34   795.4  945.72
   824.7  952.69   863.7   958.2   873.5  960.86   912.5  961.62   961.4  970.03
#Mann= 3 , 0 , 0
       0      .1       0   436.5    .045       0   451.5      .1       0
Bank Sta=436.5,451.5
XS Rating Curve= 0 ,0
Exp/Cntr=0.3,0.1

Type RM Length L Ch R = 1 ,6849.6  ,388.7,400,417.216
XS GIS Cut Line= 3
     1759926.857      342421.153     1760328.018      342206.727
     1760743.853      341991.138
#Sta/Elev= 30
       0 1012.86    19.4 1004.95    87.1  985.65    96.8  984.38   116.1  976.35
   135.5   971.6   154.9  963.47   193.6  951.62   203.2  947.61   232.3  928.43
     242  925.72   261.3  922.48     300  921.71   309.7   919.7   338.7  918.63
   367.8  915.35   447.4  915.35   462.4  915.35   513.4  921.91     572  921.94
   591.5   925.2   620.8   925.2   640.3   928.1   679.3  928.61   796.4  941.89
   806.2  944.15   845.2  941.83     855  943.16   884.2   952.6   923.3  961.95
#Mann= 3 , 0 , 0
       0      .1       0   447.4    .045       0   462.4      .1       0
Bank Sta=447.4,462.4
XS Rating Curve= 0 ,0
Exp/Cntr=0.3,0.1

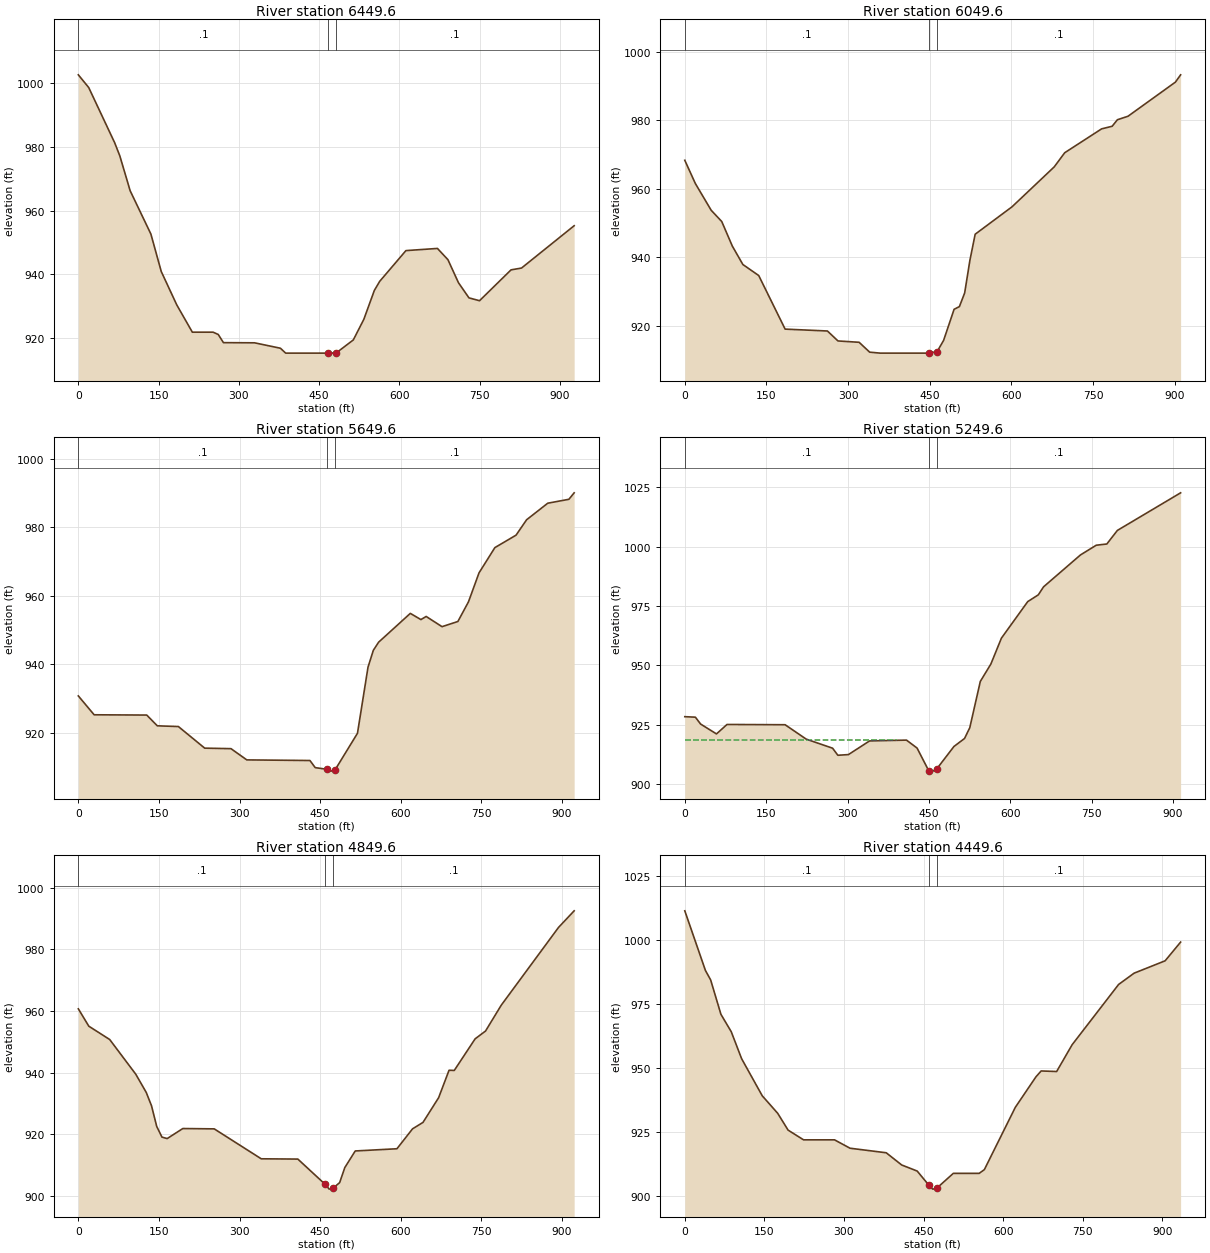
Type RM Length L Ch R = 1 ,6449.6  ,394.845,400,400.301
XS GIS Cut Line= 3
     1759970.665      342554.876     1760445.036      342564.089
     1760878.542      342691.367
#Sta/Elev= 30
       0 1002.49    19.4  998.51    67.8  981.26    77.5  977.12    96.8   966.2
   135.6  952.62   154.9  940.91     184  930.42     213  921.91   251.8  921.91
   261.4  921.19   271.1  918.63   329.2  918.58   377.6  916.88   387.3  915.35
     467  915.35     482  915.44   513.7  919.48   533.4  925.94     553  934.97
   562.9   937.8     612  947.45   670.9  948.13   690.5  944.61   710.2  937.39
   729.8  932.65   749.5  931.76   808.4  941.42     828  941.99   926.3  955.24
#Mann= 3 , 0 , 0
       0      .1       0     467    .045       0     482      .1       0
Bank Sta=467,482
XS Rating Curve= 0 ,0
Exp/Cntr=0.3,0.1

Type RM Length L Ch R = 1 ,6049.6  ,393.631,400,402.357
XS GIS Cut Line= 3
     1759951.124      342847.855     1760394.035      342956.345
      1760828.48       343090.96
#Sta/Elev= 30
       0  968.29    19.4  961.51    48.5  953.71    67.9  950.43    87.3  943.28
   106.7   937.9   135.8  934.69   184.3  919.07     262  918.52   281.4  915.62
   320.2  915.23   339.6  912.35     359  912.07   448.5  912.07   463.5  912.51
   475.4  915.78   494.7  924.85   504.4  925.63   514.1  929.61   523.7  939.11
   533.4  946.73   601.2  954.74   678.6  966.36   697.9  970.49   765.7  977.45
     785   978.2   794.7  980.11   814.1  981.12   901.2  991.07   910.8   993.2
#Mann= 3 , 0 , 0
       0      .1       0   448.5    .045       0   463.5      .1       0
Bank Sta=448.5,463.5
XS Rating Curve= 0 ,0
Exp/Cntr=0.3,0.1

Type RM Length L Ch R = 1 ,5649.6  ,386.811,400,417.556
XS GIS Cut Line= 3
     1759874.472      343105.535     1760281.853      343340.145
     1760697.579      343518.408
#Sta/Elev= 30
       0  930.75    29.4  925.24   127.3  925.16   146.9  922.02   186.1  921.81
   235.1   915.5     284  915.35   313.4  912.07   430.9  911.89   440.7  909.81
   462.6  909.32   470.1  908.79   477.6  909.15   519.3  919.84   538.9  939.14
   548.8  944.06   558.6  946.43   617.6  954.85   637.3  953.04   647.1  953.95
   676.6  950.97   706.1  952.48   725.8  958.22   745.4  966.67   774.9  974.05
   814.3  977.69   833.9  982.18   873.3  987.02   912.6  988.16   922.4  990.05
#Mann= 3 , 0 , 0
       0      .1       0   462.6    .045       0   477.6      .1       0
Bank Sta=462.6,477.6
XS Rating Curve= 0 ,0
Exp/Cntr=0.3,0.1

Type RM Length L Ch R = 1 ,5249.6  ,404.493,400,394.121
XS GIS Cut Line= 3
     1759790.833      343182.005     1759995.506      343590.912
      1760168.38      344013.519
#Sta/Elev= 30
       0  928.48    19.5  928.27    29.2  925.37    58.4  921.23    77.8   925.2
   184.9  925.09   223.8  919.04   272.4  915.23   282.1  912.26   301.6  912.54
   340.5  918.28   408.6  918.63   428.1  915.29   449.8  905.68   457.3  905.59
   464.8  906.64   496.1  915.95   515.6  919.31   525.3  923.85   544.7   943.3
   564.1  950.58   583.6  961.49   632.1  976.85   651.6   979.7   661.3  983.07
   729.3  996.47   758.4 1000.56   777.9 1001.07   797.3 1006.77   913.9 1022.58
#Mann= 3 , 0 , 0
       0      .1       0   449.8    .045       0   464.8      .1       0
#XS Ineff= 2 , 0
          390.61  918.61
Permanent Ineff=
       F       F
Bank Sta=449.8,464.8
XS Rating Curve= 0 ,0
Exp/Cntr=0.3,0.1

Type RM Length L Ch R = 1 ,4849.6  ,403.149,400,401.751
XS GIS Cut Line= 3
     1759378.139      343429.485     1759670.374      343793.559
     1759949.613      344153.869
#Sta/Elev= 30
       0  960.73    19.5   955.1    58.4  950.77     107  939.49   126.4   933.6
   136.2  929.27   145.9  922.57   155.6  919.11   165.3  918.63   194.5  921.89
   252.9  921.78   340.4  912.07   408.5  911.98   459.4  903.77   466.9  902.23
   474.4  902.59   486.3  904.34   495.9  909.22   515.3  914.61   592.9  915.33
     622   921.8   641.4  923.88   670.5   931.9   689.9   940.8   699.6  940.74
   738.4  950.99   757.8  953.53   786.9  961.88   893.6  987.14   922.7  992.53
#Mann= 3 , 0 , 0
       0      .1       0   459.4    .045       0   474.4      .1       0
Bank Sta=459.4,474.4
XS Rating Curve= 0 ,0
Exp/Cntr=0.3,0.1

Type RM Length L Ch R = 1 ,4449.6  ,406.02,400,393.658
XS GIS Cut Line= 3
     1759019.549       343676.96     1759370.721      343985.247
     1759652.733      344357.957
#Sta/Elev= 30
       0 1011.54    38.9   988.2    48.7  984.52    68.1  971.05    87.6  964.21
   107.1  953.67     146  939.15   175.2  932.28   194.7  925.72   223.9  921.91
   282.3  921.91   311.5  918.63   379.7  916.85   408.9  912.07   438.1  909.69
   459.8  904.24   467.3  902.62   474.8  902.95   506.2  908.79   554.9  908.79
   564.7  910.25   623.1  934.64     662  946.58   671.8  948.87     701  948.65
   730.2  959.14   817.8  982.72     847  987.14   905.5  991.98   934.7   999.3
#Mann= 3 , 0 , 0
       0      .1       0   459.8    .045       0   474.8      .1       0
Bank Sta=459.8,474.8
XS Rating Curve= 0 ,0
Exp/Cntr=0.3,0.1

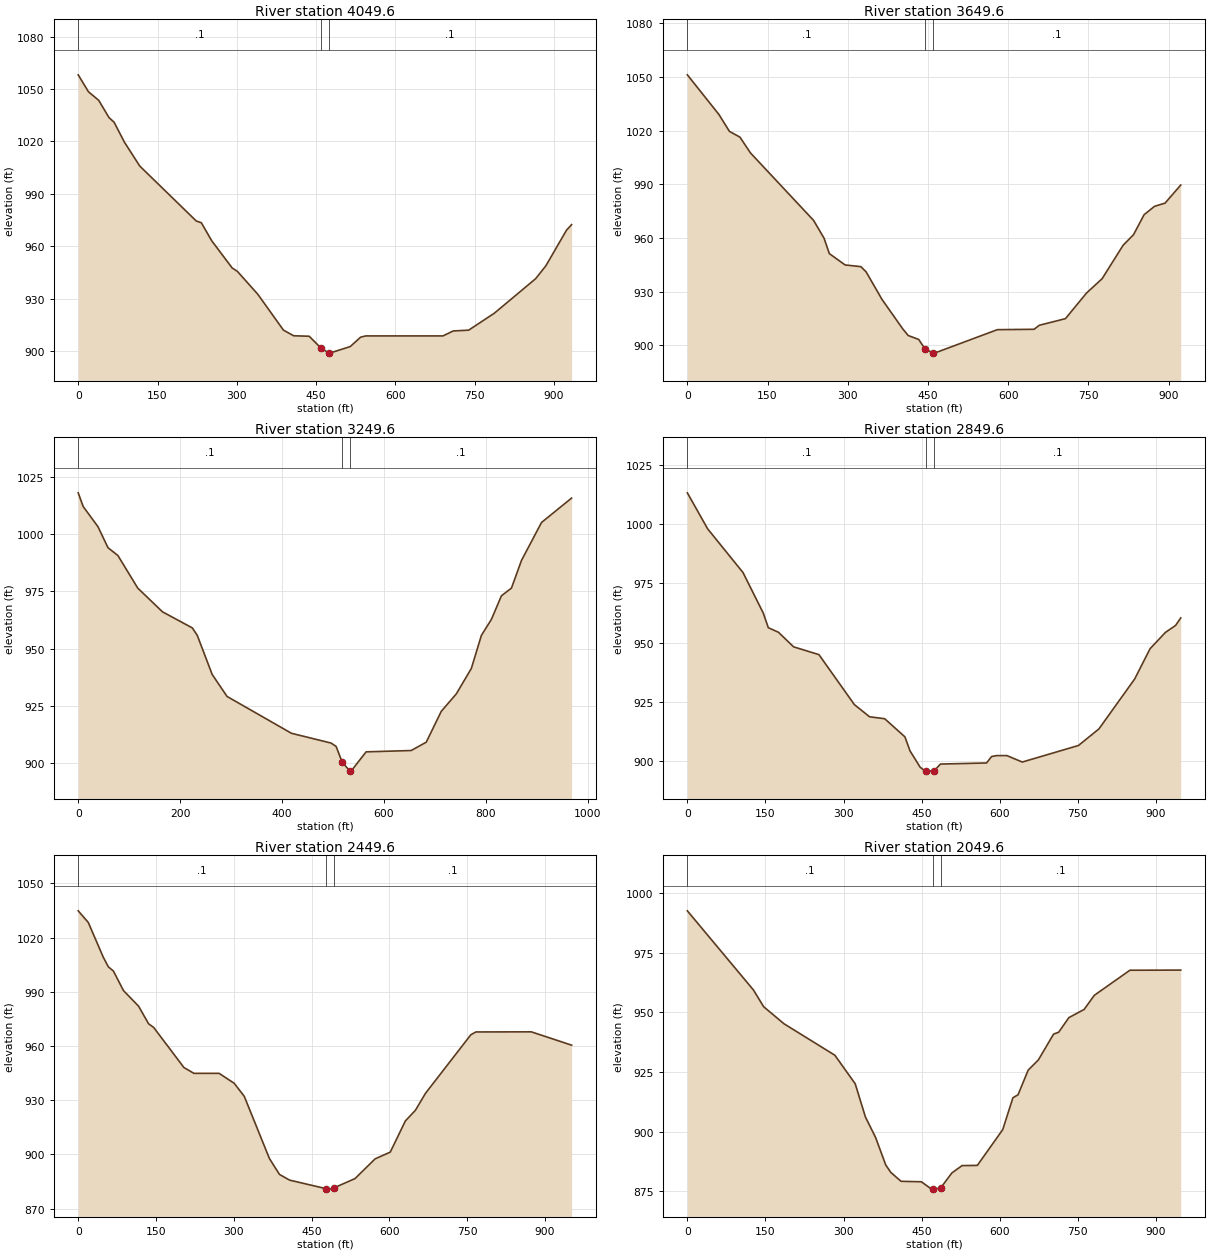
Type RM Length L Ch R = 1 ,4049.6  ,388.436,400,401.014
XS GIS Cut Line= 3
      1758692.53      344023.501     1759110.846      344228.818
     1759477.641       344518.61
#Sta/Elev= 30
       0 1058.09    19.4 1048.41    38.8  1043.5    58.2 1033.67      68 1030.93
    87.4  1019.6   116.5 1005.91   223.3  974.52     233  973.49   252.4  963.29
   291.2  947.66     301  945.74   339.8  932.61   388.3  912.09   407.7  908.87
   436.9  908.61   458.5   902.1   473.5  899.07   475.7  898.95   514.7  902.71
   534.2  908.06   543.9  908.79     690  908.79   709.5  911.63   738.7  912.08
   787.4  921.82   865.3   941.5   884.8  948.92   923.7  969.23   933.4  972.43
#Mann= 3 , 0 , 0
       0      .1       0   458.5    .045       0   473.5      .1       0
Bank Sta=458.5,473.5
XS Rating Curve= 0 ,0
Exp/Cntr=0.3,0.1

Type RM Length L Ch R = 1 ,3649.6  ,402.434,400,398.972
XS GIS Cut Line= 3
     1758579.047      344130.027     1758836.232      344502.091
     1759184.331      344818.331
#Sta/Elev= 30
       0 1051.15      59 1029.02    78.7 1019.56    98.3 1016.35     118 1007.53
     236  969.84   255.6   959.9   265.5  951.27     295  944.94   324.5  943.98
   334.3  941.07   363.8  925.76   403.1  909.08     413  905.51   432.6  903.31
   444.8  897.89   459.8  895.75   462.1  895.67   579.7  908.78   648.3  908.98
   658.1  911.23     707  914.93   746.2  929.17   775.6  937.26   814.8  955.92
   834.4  961.88     854  972.98   873.6  977.69   893.2  979.46   922.6  989.57
#Mann= 3 , 0 , 0
       0      .1       0   444.8    .045       0   459.8      .1       0
Bank Sta=444.8,459.8
XS Rating Curve= 0 ,0
Exp/Cntr=0.3,0.1

Type RM Length L Ch R = 1 ,3249.6  ,388.562,400,415.949
XS GIS Cut Line= 3
     1758309.208      344420.877     1758661.867      344810.513
     1759008.158      345086.077
#Sta/Elev= 30
       0 1017.93     9.7 1011.98    38.9 1003.12    58.4     994    77.9  990.58
   116.8  976.38   165.4  966.01   223.8  959.02   233.6  955.77   262.8  938.72
     292  929.11   418.5  913.02   496.3  908.76   506.1  907.28     518  900.38
     533  896.63   535.4  896.52   564.9  904.93   653.4  905.51   682.9  909.15
   712.4  922.62   741.9  930.22   771.4  941.33   791.1  955.74   810.7   962.7
   830.4     973   850.1  976.37   869.7  988.41   909.1    1005   968.1 1015.64
#Mann= 3 , 0 , 0
       0      .1       0     518    .045       0     533      .1       0
Bank Sta=518,533
XS Rating Curve= 0 ,0
Exp/Cntr=0.3,0.1

Type RM Length L Ch R = 1 ,2849.6  ,388.654,400,413.1
XS GIS Cut Line= 3
     1758212.606      344465.581     1758310.498      344921.673
     1758396.581      345394.893
#Sta/Elev= 30
       0 1013.22    38.9  998.04   106.9  979.54   145.8  962.43   155.5  956.25
   174.9  954.33   204.1  948.16   252.7  944.88   320.7  923.78   349.9  918.63
     379   917.8   417.9  910.13   427.6  904.23     447  897.35   456.8  895.67
     459  895.67     474  895.83   486.1  898.66   574.5  899.11   584.3  901.84
   594.1  902.23   613.7  902.23   643.2  899.51   751.1   906.5   790.4   913.5
   859.1  934.61   888.6  947.38     918  954.25   937.6  957.21   947.5   960.4
#Mann= 3 , 0 , 0
       0      .1       0     459    .045       0     474      .1       0
Bank Sta=459,474
XS Rating Curve= 0 ,0
Exp/Cntr=0.3,0.1

Type RM Length L Ch R = 1 ,2449.6  ,409.891,400,390.536
XS GIS Cut Line= 3
     1758110.741       344462.15     1757969.732      344926.337
     1757772.346        345348.8
#Sta/Elev= 30
       0  1034.8    19.4 1028.39    48.5 1009.04    58.2 1003.81    67.9 1001.48
    87.3  990.68   116.4  982.05   135.8  972.29   145.5  970.29   203.8  948.12
   223.2  944.88   271.7  944.88   300.8  939.39   320.2  932.18   368.7  897.78
   388.1  888.96   407.5  885.82   477.6  881.11   485.1  880.83   492.6  881.46
   533.7  886.65   572.6  897.59   601.7  901.29   630.9  918.57   650.3  924.47
   669.7  933.86   757.1  966.24   766.9  967.79   873.7  967.85   951.4  960.48
#Mann= 3 , 0 , 0
       0      .1       0   477.6    .045       0   492.6      .1       0
Bank Sta=477.6,492.6
XS Rating Curve= 0 ,0
Exp/Cntr=0.3,0.1

Type RM Length L Ch R = 1 ,2049.6  ,387.935,400,405.609
XS GIS Cut Line= 3
     1757587.248      344366.823      1757642.81      344842.504
     1757638.971      345311.499
#Sta/Elev= 30
       0  992.48   127.1  959.31   146.6  952.34   185.7   945.2   283.4  932.03
   322.5  920.08   342.1  906.19   361.6  897.63   381.2  886.07     391  882.95
   410.5  879.26   449.6  879.06   469.1  875.98   471.4  875.99   486.4  876.39
   508.2  882.76   527.8  885.83   557.1  885.91   605.9  900.89   625.5  914.23
   635.3  915.47   654.8   925.8   674.3  930.05   703.6  940.87   713.4  941.67
     733  947.78   762.3   951.2   781.8   957.1   850.2  967.61   947.9  967.67
#Mann= 3 , 0 , 0
       0      .1       0   471.4    .045       0   486.4      .1       0
Bank Sta=471.4,486.4
XS Rating Curve= 0 ,0
Exp/Cntr=0.3,0.1