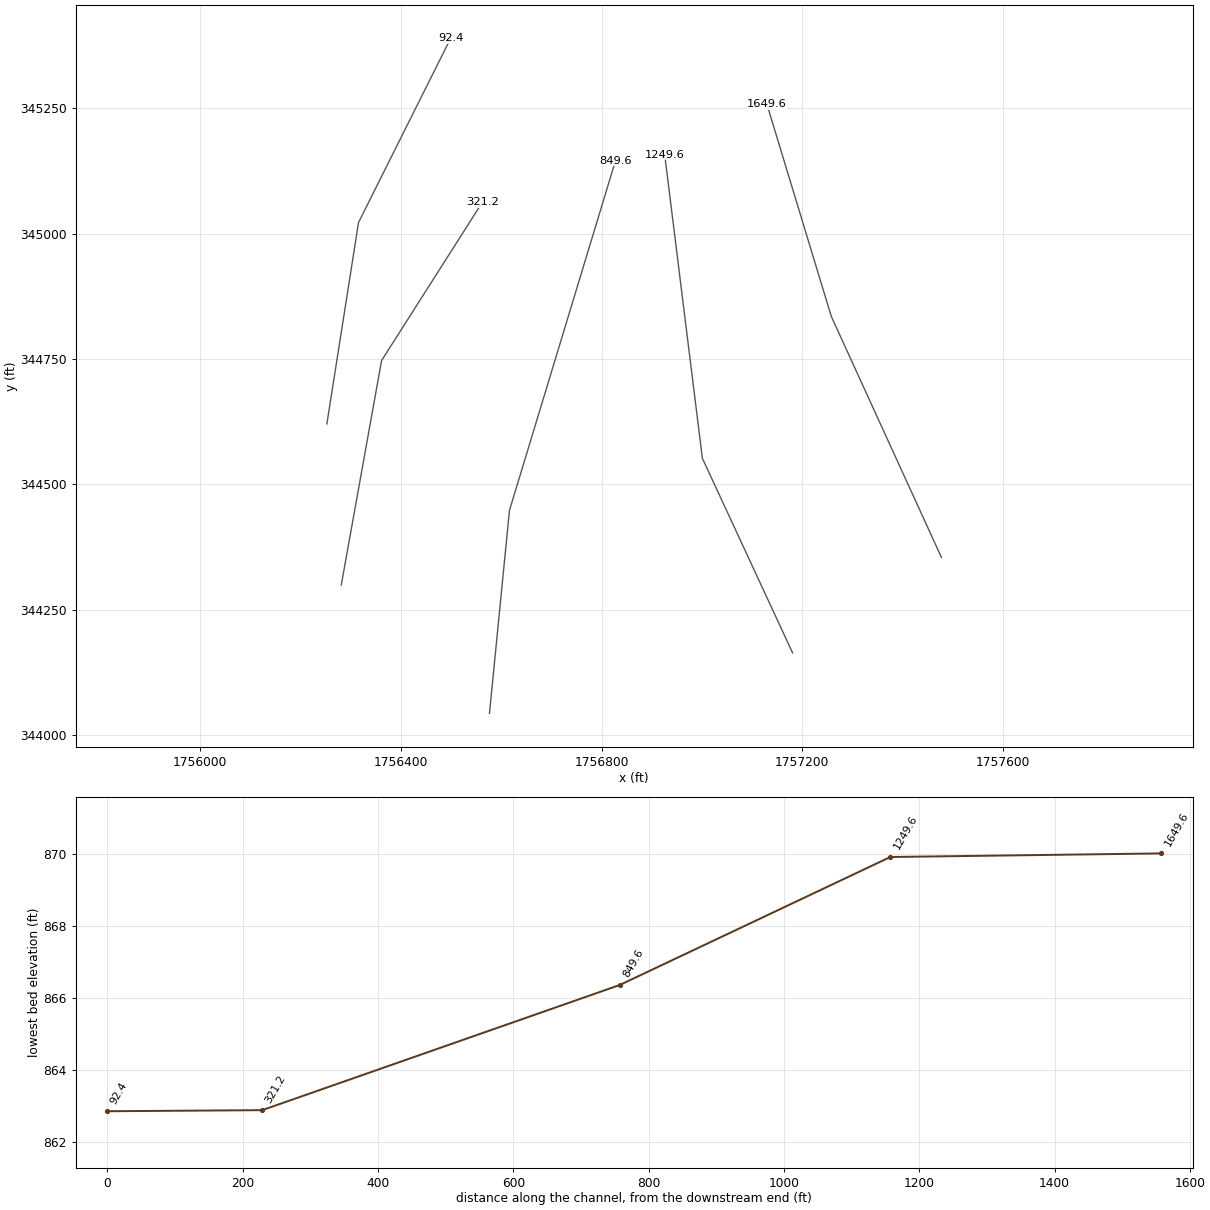
HEC-RAS study CnsRn.prj: CnsRn

--- CnsRn.g01 (geometry) --- (continued)

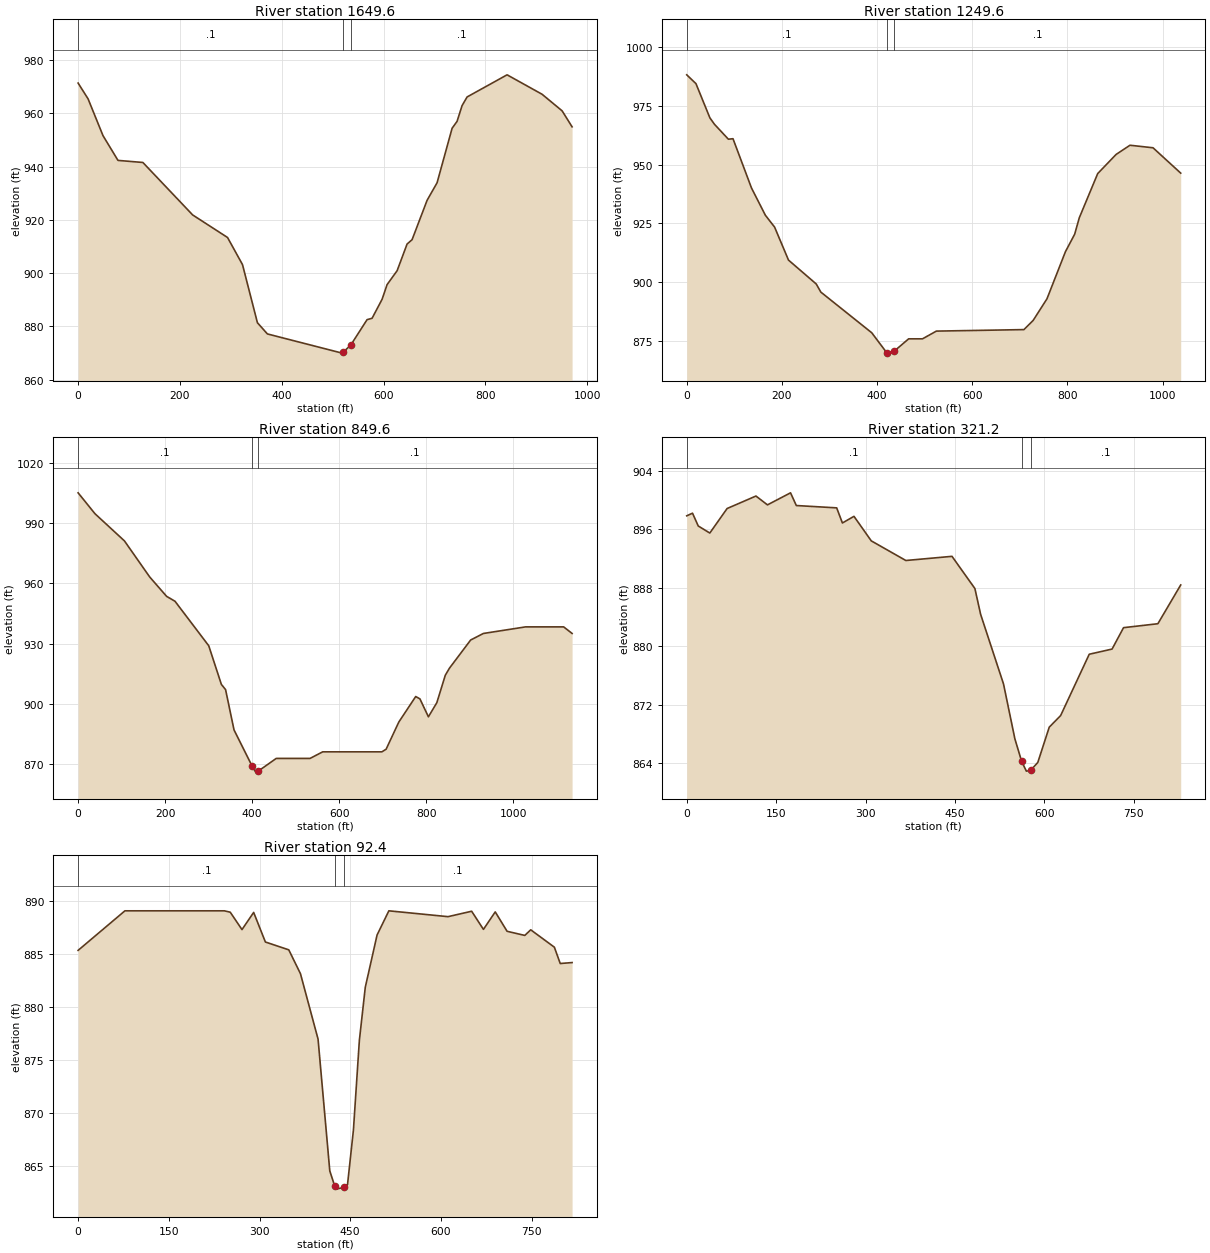
Type RM Length L Ch R = 1 ,1649.6  ,400.36,400,395.475
XS GIS Cut Line= 3
     1757477.277      344354.185     1757257.721      344834.744
     1757129.426      345257.675
#Sta/Elev= 30
       0  971.31    19.6  965.39    48.9  951.59    78.3  942.31   127.2  941.53
     225  921.85   293.5  913.39   322.9  903.22   352.2  881.42   371.8  877.21
   518.6  870.01   520.8  870.37   535.8   873.1   567.6  882.57   577.4  883.08
   597.1  890.21   606.9  895.71   626.6  900.92   646.2  910.94     656  912.56
   685.5  927.34   705.1  933.92   734.6  954.35   744.4  956.97   754.2  962.86
   764.1  966.11   842.6  974.41   911.4  967.11   950.7   960.9   970.3   954.9
#Mann= 3 , 0 , 0
       0      .1       0   520.8    .045       0   535.8      .1       0
Bank Sta=520.8,535.8
XS Rating Curve= 0 ,0
Exp/Cntr=0.3,0.1

Type RM Length L Ch R = 1 ,1249.6  ,412.042,400,390.691
XS GIS Cut Line= 3
     1757180.582      344163.994     1757000.792      344551.962
     1756925.635      345157.574
#Sta/Elev= 30
       0  988.09    19.4  984.34    48.6  969.84    58.3  967.08    87.5  960.75
    97.2  960.96   136.1  940.02   165.2  928.47   184.6  923.43   213.8  909.42
   272.1  899.27   281.8  895.82   388.7  878.56   420.1  870.12   427.6  869.91
   435.1  870.61   466.3  875.98   495.4  875.98   524.5  879.26   708.5   879.9
   727.9  883.81   756.9  892.98   795.7  912.99   815.1  920.42   824.8  927.38
   863.5  946.16   902.2  954.29   931.3  958.19   979.7  957.11  1037.9  946.35
#Mann= 3 , 0 , 0
       0      .1       0   420.1    .045       0   435.1      .1       0
Bank Sta=420.1,435.1
XS Rating Curve= 0 ,0
Exp/Cntr=0.3,0.1

Type RM Length L Ch R = 1 ,849.6   ,537.105,528.376,524.134
XS GIS Cut Line= 3
     1756576.468      344043.512     1756616.332      344448.249
     1756827.676      345145.473
#Sta/Elev= 30
       0 1005.19    38.7  994.78   106.5   981.2   164.6  963.19   203.3  953.56
   222.7  951.09   300.2   928.9   329.2  909.64   338.9  907.01   358.3  886.92
   399.2  869.16   406.7  866.36   414.2   866.4   455.3   872.7     533   872.7
   562.1  875.98   698.1  875.98   707.8  877.29     737  890.84   775.8  903.57
   785.5  902.41     805  893.46   824.4  900.52   843.8  914.18   853.5  917.76
   902.1  931.76   931.3  935.03  1028.4  938.32  1115.8  938.32  1135.2  935.04
#Mann= 3 , 0 , 0
       0      .1       0   399.2    .045       0   414.2      .1       0
Bank Sta=399.2,414.2
XS Rating Curve= 0 ,0
Exp/Cntr=0.3,0.1

Type RM Length L Ch R = 1 ,321.2   ,228.81,228.82,228.831
XS GIS Cut Line= 3
     1756281.099      344299.368     1756361.404      344746.779
     1756562.165       345062.26
#Sta/Elev= 30
       0  897.86     9.7  898.22    19.3  896.47    38.7   895.5    67.7  898.86
   116.1  900.57   135.4  899.36   174.1  901.01   183.8  899.27   251.5  898.95
   261.1  896.88   280.5  897.79   309.5  894.43   367.5  891.74   444.9  892.31
   483.3   887.9   492.9  884.37   531.3  874.83   550.4   867.3   561.7  864.23
   569.6  862.89   576.7  862.99   588.8  864.08     608  868.91   627.1   870.5
   675.1   878.9   713.4  879.61   732.6  882.54   790.2  883.08   828.5  888.39
#Mann= 3 , 0 , 0
       0      .1       0   561.7    .045       0   576.7      .1       0
Bank Sta=561.7,576.7
XS Rating Curve= 0 ,0
Exp/Cntr=0.3,0.1

Type RM Length L Ch R = 1 ,92.4    ,91.862,92.396,92.93
XS GIS Cut Line= 3
     1756252.419      344620.586     1756315.516      345022.108
     1756499.068      345389.214
#Sta/Elev= 30
       0  885.38    77.4  889.11   241.9  889.11   251.6  888.98     271  887.34
   290.3  888.96   309.7  886.17   348.4  885.43   367.7  883.18   396.8  877.01
   416.2  864.58   424.4  863.14     426  862.86   439.4  863.02   445.5  863.28
   455.3  868.44   465.1  876.88   474.9   881.9   494.4  886.83   513.9  889.11
   611.7  888.56   650.8  889.07   670.3  887.36   689.8  889.01   709.4  887.18
   738.7  886.79   748.5  887.32   787.6  885.68   797.3  884.14   816.9  884.23
#Mann= 3 , 0 , 0
       0      .1       0   424.4    .045       0   439.4      .1       0
Bank Sta=424.4,439.4
XS Rating Curve= 0 ,0
Exp/Cntr=0.3,0.1

Chan Stop Cuts=-1
Use User Specified Reach Order=0